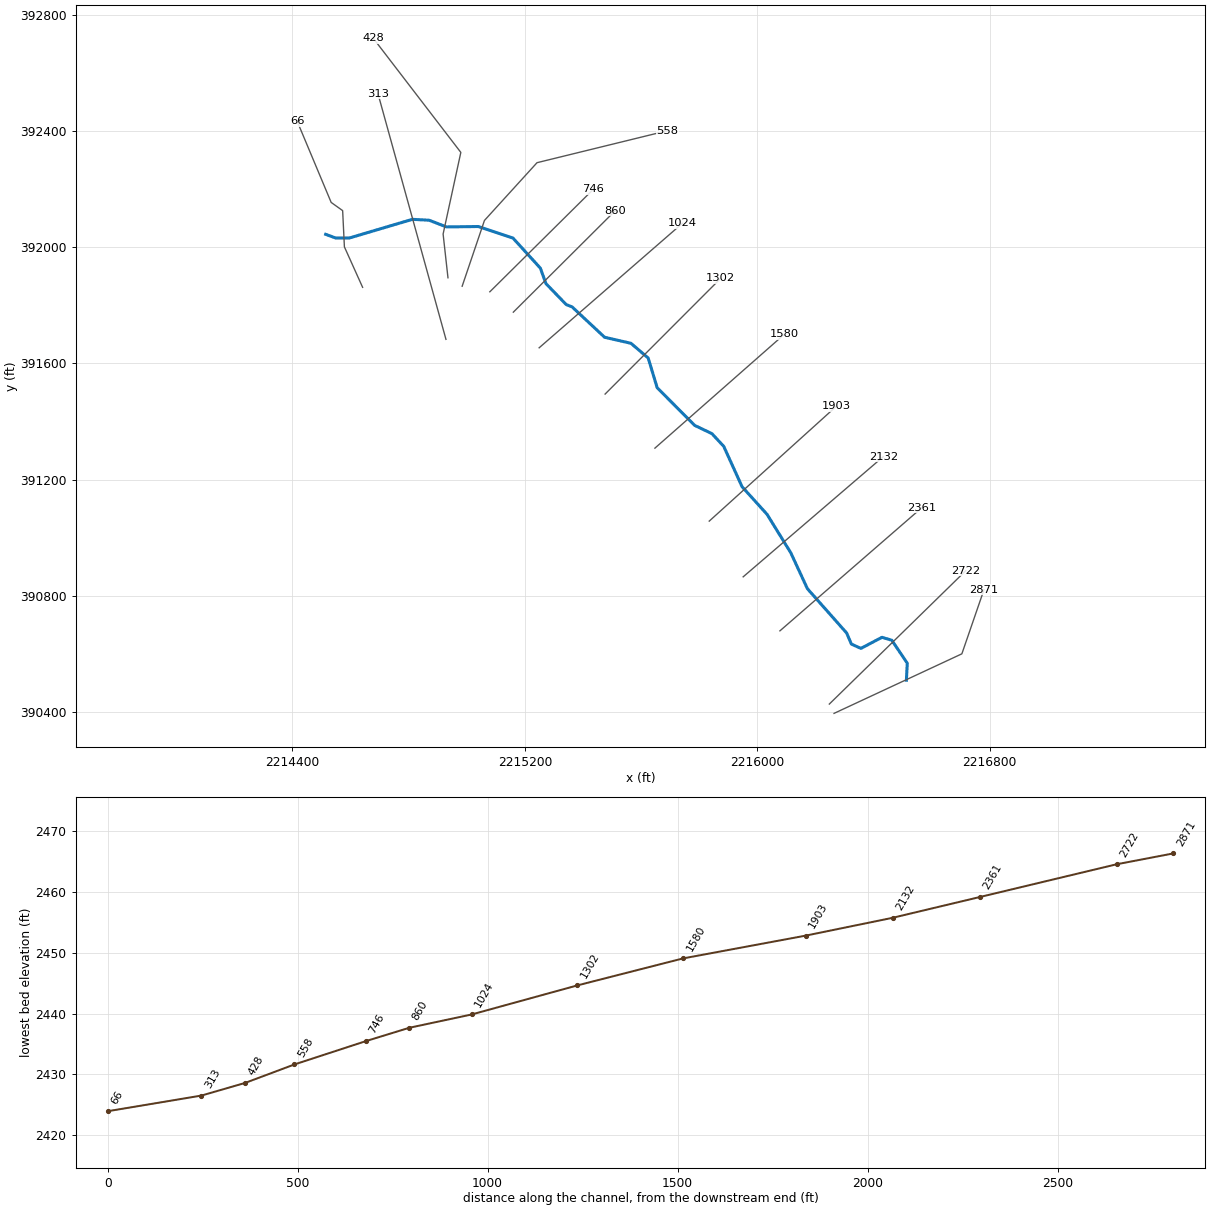
--- LAURELRNT1.prj (project) ---

Proj Title=LAURELRNT1
Current Plan=p01
Default Exp/Contr=0,0
English Units
Geom File=g01
Flow File=f01
Plan File=p01
Background Map Layer=Inundation Boundary (01pct Value_0)
BEGIN DESCRIPTION:
----------MODEL BY WOOD PLC 2021----------
Stream Name: Laurel Run Tributary 1
Flood Zone: Enhanced Approximate
Pocahontas County, WV
HEC-RAS Version: RAS 6.1
Vertical Datum: NAVD88
Projection: NAD 1983 StatePlane West Virginia S FIPS 4702 (US Feet)
Terrain: 1-meter LIDAR (FEMA Region III 3DEP collected 2016-2018)
Land Use: 2019 NLCD
Hydrologic Method:
WV SIR2010-5033 regression equations
Model Notes:
Normal depth tie in to Laurel Run
END DESCRIPTION:
DSS Export Rating Curves= 0
DSS Export Rating Curve Sorted= 0
DSS Export Volume Flow Curves= 0
DXF OffsetX= 0
DXF OffsetY= 0
DXF ScaleX= 0
DXF ScaleY= 0

--- LAURELRNT1.p01 (plan) ---

Plan Title=Floodplain
Program Version=6.00
Short Identifier=Floodplain
Geom File=g01
Flow File=f01
Subcritical Flow
K Sum by GR= 0
Std Step Tol= 0.01
Critical Tol= 0.01
Num of Std Step Trials= 20
Max Error Tol= 0.3
Flow Tol Ratio= 0.001
Split Flow NTrial= 30
Split Flow Tol= 0.02
Split Flow Ratio= 0.02
Log Output Level= 0
Friction Slope Method= 1
Unsteady Friction Slope Method= 2
Unsteady Bridges Friction Slope Method= 1
Parabolic Critical Depth
Global Vel Dist= 0 , 0 , 0
Global Log Level= 0
CheckData=False
Encroach Param=-1 ,0,0, 0
Mapping Interval=1HOUR
Computation Time Step Use Courant=        0
Computation Time Step Use Time Series=    0
Computation Time Step Count To Double=0
Computation Time Step Max Doubling=0
Computation Time Step Max Halving=0
Computation Time Step Residence Courant=0
Run HTab= 0
Run UNet= 0
Run Sediment= 0
Run PostProcess= 0
Run WQNet= 0
Run RASMapper=-1
UNET Theta= 0
UNET Theta Warmup= 0
UNET ZTol= 0
UNET ZSATol= 0
UNET MxIter= 0
UNET Max Iter WO Improvement= 0
UNET MaxInSteps= 0
UNET DtIC= 0
UNET DtMin= 0
UNET MaxCRTS= 0
UNET WFStab= 0
UNET SFStab= 0
UNET WFX= 1
UNET SFX= 1
UNET Gravity=32.174
UNET 1D Methodology=Finite Difference
UNET DSS MLevel= 1
UNET Pardiso=0
UNET DZMax Abort= 0
UNET Use Existing IB Tables= 0
UNET Froude Reduction=False
UNET Froude Limit= 0
UNET Froude Power= 0
UNET D1 Cores= 0
UNET WindReference=Eulerian
UNET WindDragFormulation=Hsu (1988)
UNET D2 Coriolis=0
UNET D2 Cores= 0
UNET D2 Theta= 1
UNET D2 Theta Warmup= 1
UNET D2 Z Tol= 0.01
UNET D2 Volume Tol= 0.01
UNET D2 Max Iterations= 20
UNET D2 Equation= 0
UNET D2 RampUpFraction=0.1
UNET D2 TimeSlices= 1
UNET D2 Turbulence Formulation=Non-Conservative (original)
UNET D2 Eddy Viscosity=0.3
UNET D2 Transverse Eddy Viscosity=0.1
UNET D2 Smagorinsky Mixing=0
UNET D2 BCVolumeCheck=0
UNET D2 Cores=0
UNET D2 SolverType=PARDISO (Direct)
UNET D2 Minimum Iterations= 2147483647
UNET D2 Maximum Iterations= 2147483647
UNET D2 Restart Number= 10
UNET D2 Relaxation Coeff=1.3
UNET D2 SOR Precondition Iterations= 10
UNET D2 ILUT Maximum Fill= 8
UNET D2 ILUT Tolerance=1E-08
UNET D1D2 MaxIter= 0
UNET D1D2 ZTol=0.01
UNET D1D2 QTol=0.1
UNET D1D2 MinQTol=1
Write IC File= 0
Write IC File at Fixed DateTime=0
Write IC File at Sim End=0
Echo Input=False
Echo Parameters=False
Echo Output=False
Write Detailed= 0
HDF Write Warmup=0
HDF Write Time Slices=0
HDF Flush=0
HDF Compression= 1
HDF Chunk Size= 1
HDF Spatial Parts= 1
HDF Use Max Rows=0
HDF Fixed Rows= 1
Calibration Method= 0
Calibration Iterations= 20
Calibration Max Change=0.05
Calibration Tolerance=0.2
Calibration Maximum=1.5
Calibration Minimum=0.5
Calibration Optimization Method= 1
WQ AD Non Conservative
WQ ULTIMATE=-1
WQ Max Comp Step=1HOUR
WQ Output Interval=15MIN
WQ Output Selected Increments= 0
WQ Output face flow=0
WQ Output face velocity=0
WQ Output face area=0
WQ Output face dispersion=0
WQ Output cell volume=0
WQ Output cell surface area=0
WQ Output cell continuity=0
WQ Output cumulative cell continuity=0
WQ Output face conc=0
WQ Output face dconc_dx=0
WQ Output face courant=0
WQ Output face peclet=0
WQ Output face adv mass=0
WQ Output face disp mass=0
WQ Output cell mass=0
WQ Output cell source sink temp=0
WQ Output nsm pathways=0
WQ Output nsm derived pathways=0
WQ Create Restart=0
WQ Fixed Restart=0
WQ System Summary=0
WQ Write To DSS=0
Sorting and Armoring Iterations= 10
XS Update Threshold= 0.02
Bed Roughness Predictor= 0
Hydraulics Update Threshold= 0.02
Energy Slope Method= 1
Volume Change Method= 1
Sediment Retention Method= 0
Sediment TS Multiplier= 1
Warm Up Method= 0
XS Weighting Method= 0
Number of US Weighted Cross Sections= 1
Number of DS Weighted Cross Sections= 1
Upstream XS Weight=0
Main XS Weight=1
Downstream XS Weight=0
Number of DS XS's Weighted with US Boundary= 1
Upstream Boundary Weight= 1
Weight of XSs Associated with US Boundary= 0
Number of US XS's Weighted with DS Boundary= 1
Downstream Boundary Weight= 0.5
Weight of XSs Associated with DS Boundary= 0.5
Percentile Method= 0
Sediment Output Level= 3
Mass or Volume Output= 0
Output Increment Type= 1
Profile and TS Output Increment= 1
Transport Output Increment 1
XS Output Flag= 0
XS Output Increment= 10
Read HDF5 Sediment Hotstart= 0
Sediment Hotstart Type= 0
Write Gradation File= 0
Read Gradation Hotstart= 0
Write HDF5 File= 1
Write Binary Output= 1
Write DSS Sediment File= 0
DSS Sediment Output Type= 1
SV Curve= 0
Specific Gage Flag= 0
Subcell Erosion Methods= 0
Subcell Deposition Methods= 0
Advection Scheme= 1
Matrix Solver= 0
Implicit Weighting Factor= 1
Maximum Outer Loop Convergence Iterations= 5
Convergence Maximum Absolute= 0.001
Convergence RMSE= 0.0001
Grain Fractions Max Abs Error= 0.001
Max Subgrid Regions= 1
Max Subgrid Length Scale= 3.402823E+38
Initial Layer Thickness= 3.402823E+38
Min Layer Thickness= 3.402823E+38
Max Layer Thickness= 3.402823E+38
Number of Layers= 5

--- LAURELRNT1.f01 (steady flow) ---

Flow Title=Flow
Program Version=6.00
Number of Profiles= 6
Profile Names=01pct,10pct,04pct,02pct,0_2pct,01plus
River Rch & RM=LAURELRNT1,Main,2871
     745     397     526     632    1030    1100
Boundary for River Rch & Prof#=LAURELRNT1,Main            , 1
Up Type= 0
Dn Type= 3
Dn Slope=0.00691
Boundary for River Rch & Prof#=LAURELRNT1,Main            , 2
Up Type= 0
Dn Type= 3
Dn Slope=0.00691
Boundary for River Rch & Prof#=LAURELRNT1,Main            , 3
Up Type= 0
Dn Type= 3
Dn Slope=0.00691
Boundary for River Rch & Prof#=LAURELRNT1,Main            , 4
Up Type= 0
Dn Type= 3
Dn Slope=0.00691
Boundary for River Rch & Prof#=LAURELRNT1,Main            , 5
Up Type= 0
Dn Type= 3
Dn Slope=0.00691
Boundary for River Rch & Prof#=LAURELRNT1,Main            , 6
Up Type= 0
Dn Type= 3
Dn Slope=0.00691
DSS Import GetInterval= 0
DSS Import GetPeak= 0
DSS Import FillOption= 0

--- LAURELRNT1.g01 (geometry) ---

Geom Title=Geometry
Program Version=6.10

River Reach=LAURELRNT1      ,Main
Reach XY= 30
 2216513.3423666390509.3742393992216516.36992849390567.671241297
2216463.13142092390646.8756450212216429.26395142390656.949944066
2216356.81974542  390618.79677582216323.93311879390633.660126628
      2216307.69      390671.732      2216172.58      390824.338
2216115.61950115390947.552862368     2216033.539      391080.571
2215947.69539096391175.434259321     2215884.494      391314.627
2215843.92129202391358.234214002     2215784.629      391386.586
     2215655.373      391516.437     2215624.548      391618.595
     2215565.111      391669.374     2215474.515      391690.105
      2215362.76      391794.4962215342.36447538391802.704320114
     2215272.607      391874.7772215253.40157097      391928.059
     2215159.061       392031.62     2215039.711      392071.433
     2214930.226      392070.033     2214870.448      392093.145
     2214812.804      392096.162     2214595.791      392031.894
     2214548.994      392031.779     2214514.265      392044.541

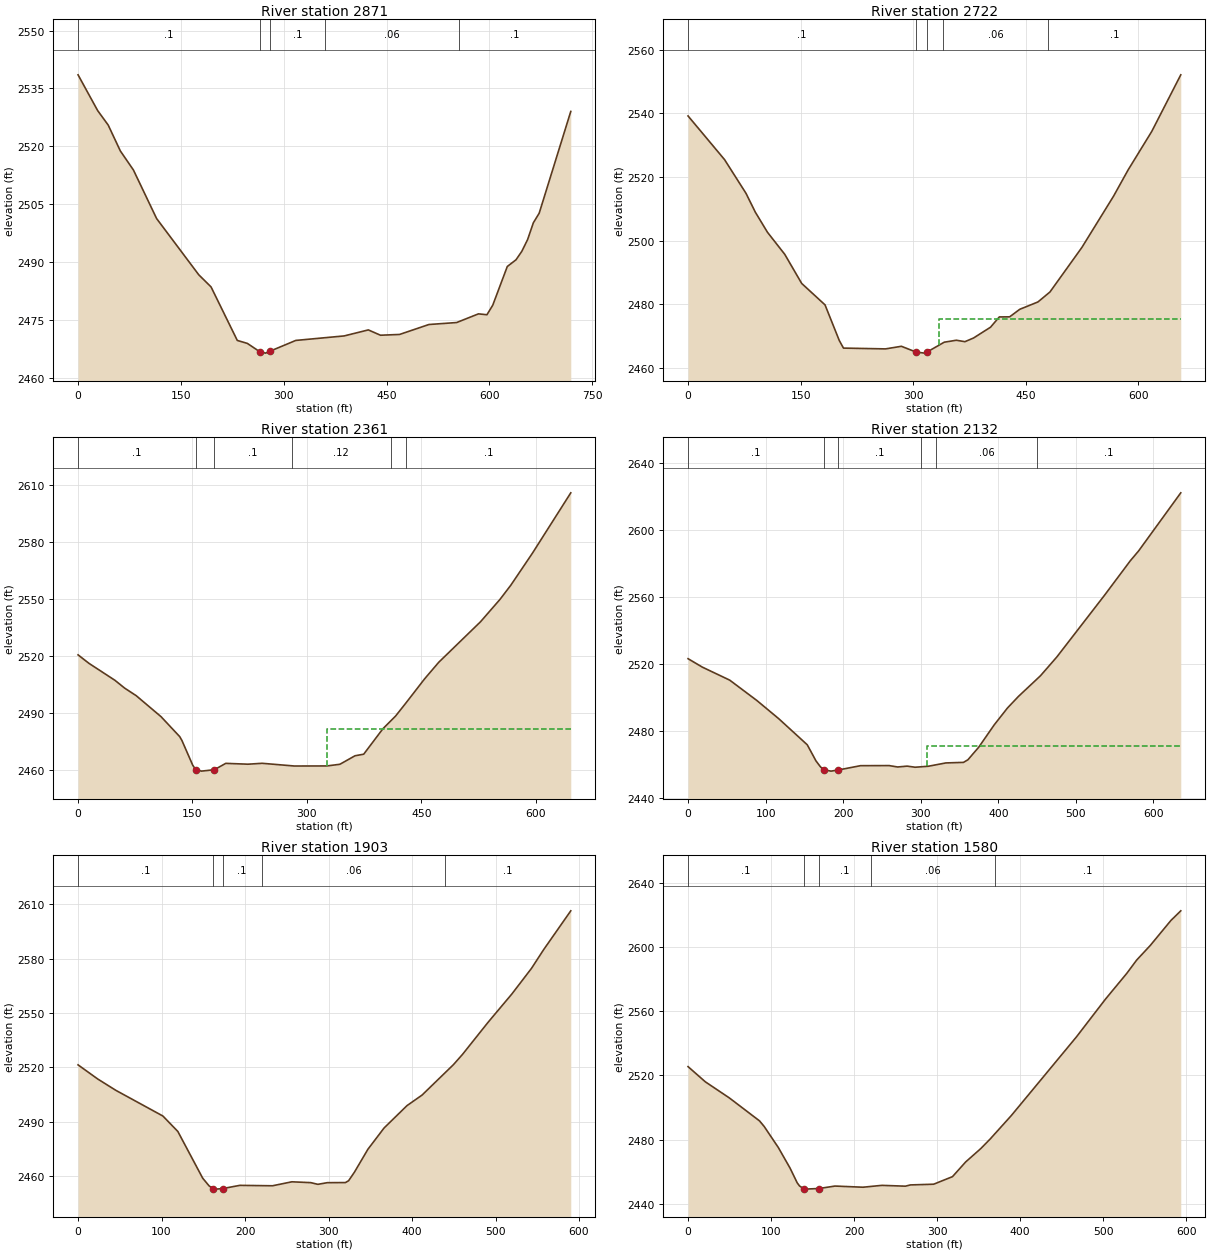
Type RM Length L Ch R = 1 ,2871    ,148.9,148.9,148.9
XS GIS Cut Line= 3
2216264.29368652390395.057376726 2216704.2530974390600.090372566
2216780.31013198390820.803519167
#Sta/Elev= 30
       0 2538.52    28.6 2529.25      44 2525.49    61.7 2518.79    80.8 2513.84
   114.6 2501.26   176.1 2486.68     194 2483.54   232.3 2469.66     247 2468.89
   264.7 2466.78   273.5 2466.37   279.6 2466.84   317.6 2469.66   388.2 2470.83
   423.5 2472.39   441.2 2471.01     469 2471.21   511.9 2473.79   552.3  2474.3
   584.1 2476.55   596.5 2476.32     605 2478.81   626.2 2488.83   638.9 2490.57
   647.3 2492.74   655.8  2495.8   664.2 2500.16   672.7 2502.64   718.8 2529.03
#Mann= 5 ,-1,0
       0      .1       0   264.7    .045       0   279.6      .1       0
     360     .06       0  555.39      .1       0
Bank Sta=264.7,279.6
XS Rating Curve= 0 ,0
Exp/Cntr=0.3,0.1

Type RM Length L Ch R = 1 ,2722    ,362.5,360.7,355
XS GIS Cut Line= 2
  2216248.025019390427.1125261732216717.62291118390886.307933391
#Sta/Elev= 30
       0 2539.16    48.7 2525.42    77.3 2514.81    89.7  2508.9   105.9 2502.58
   128.9 2495.66   151.5  2486.5   182.6 2479.76   201.6 2468.55   207.2 2466.17
   263.2 2465.92   284.4 2466.74   304.2  2464.9   315.5 2464.59   319.1    2465
   341.5 2468.03   357.7 2468.64   369.1 2468.19   380.6 2469.35   403.2 2472.74
   414.9 2475.97   428.7    2476   442.2 2478.37   466.4 2480.68   482.4 2483.81
   524.9 2497.79   567.3 2513.98   586.5 2522.15   618.2 2534.33   656.8 2552.09
#Mann= 5 ,-1,0
       0      .1       0   304.2    .045       0   319.1      .1       0
     340     .06       0     480      .1       0
#XS Ineff= 2 , 0
                          334.41         2475.26
Permanent Ineff=
       F       F
Bank Sta=304.2,319.1
XS Rating Curve= 0 ,0
Exp/Cntr(USF)=0,0
Exp/Cntr=0.3,0.1

Type RM Length L Ch R = 1 ,2361    ,229,229.6,227.5
XS GIS Cut Line= 2
2216078.00787101390679.2320985632216565.64579164391102.666170473
#Sta/Elev= 30
       0  2520.4    14.3 2515.93    48.3 2507.02    61.1 2502.88    76.2 2498.92
   108.8 2487.85   133.3 2477.33   136.2 2475.27   150.4 2462.24  154.282459.973
   161.8 2459.19   178.7 2459.94   193.6 2463.28   222.6 2462.84   241.3 2463.31
   283.6 2461.88   326.3 2461.92   343.2  2462.8     363 2467.27   374.4  2468.1
   399.5 2481.47   416.1 2488.15     430 2495.19   454.4 2507.86   472.7 2516.47
   527.5 2537.82     553 2549.59   567.2 2557.06   595.5  2573.9   645.8  2605.7
#Mann= 6 ,-1,0
       0      .1       0  154.28    .045       0   178.7      .1       0
     280     .12       0     410     .06       0     430      .1       0
#XS Ineff= 2 , 0
                          326.88         2481.36
Permanent Ineff=
       F       F
Bank Sta=154.28,178.7
XS Rating Curve= 0 ,0
Exp/Cntr=0.3,0.1

Type RM Length L Ch R = 1 ,2132    ,228.7,228.5,228.4
XS GIS Cut Line= 2
2215951.43468654390865.1825429692216433.43585622391278.819572551
#Sta/Elev= 30
       0    2523    18.4 2517.96    53.7 2510.18    88.5 2498.08   116.9 2487.13
   153.7 2471.51     165 2461.83   170.7 2458.35   174.9 2456.58   184.3 2455.77
   193.4 2456.43   222.4 2459.03   259.3 2459.08   270.2 2458.25   282.5 2458.76
   292.7  2458.1   309.7 2458.68   332.4 2460.67   355.1    2461   360.8 2462.57
   374.7 2470.05   394.8  2483.5   411.8 2493.53     426 2500.47   454.3 2512.78
   475.4 2524.02   536.7 2560.81   570.2 2581.59   580.8 2587.41   635.2 2622.18
#Mann= 6 ,-1,0
       0      .1       0   174.9    .045       0   193.4      .1       0
     300     .12       0     320     .06       0     450      .1       0
#XS Ineff= 2 , 0
                          307.53         2470.88
Permanent Ineff=
       F       F
Bank Sta=174.9,193.4
XS Rating Curve= 0 ,0
Exp/Cntr=0.3,0.1

Type RM Length L Ch R = 1 ,1903    ,321.9,322.9,321.9
XS GIS Cut Line= 2
2215834.63067066 391057.045683592216272.40386448391452.692665034
#Sta/Elev= 30
       0 2521.42    23.6 2513.61    45.2 2507.38   101.6 2493.19   119.5 2484.67
   149.3 2458.87   156.9 2454.65   161.3 2453.17   165.4 2452.84   173.2 2453.15
   193.8 2454.92   232.9 2454.69   256.1 2456.88   278.7 2456.42   287.2 2455.49
   298.5  2456.4   320.2 2456.46     324 2457.47     331  2462.2   347.1 2474.81
   366.5 2486.58   393.9  2498.9     412 2504.75   449.6 2521.55   460.4 2527.18
   491.1 2544.94   519.5 2560.51   543.1  2574.7   557.4 2584.87   590.1 2606.43
#Mann= 5 ,-1,0
       0      .1       0   161.3    .045       0   173.2      .1       0
     220     .06       0     440      .1       0
Bank Sta=161.3,173.2
XS Rating Curve= 0 ,0
Exp/Cntr(USF)=0,0
Exp/Cntr=0.3,0.1

Type RM Length L Ch R = 1 ,1580    ,277.6,278.6,278.8
XS GIS Cut Line= 2
2215647.65677427391308.3143430642216093.06627531391700.228442107
#Sta/Elev= 30
       0 2525.44    20.8 2515.98    49.8 2505.91    86.1 2491.61    91.7 2488.12
   108.7 2475.03   122.9 2462.13   131.4 2453.05   134.2 2451.08   139.2 2449.39
   140.6 2449.09   157.8 2449.48   176.9    2451   210.7 2450.28   233.4 2451.44
   261.7 2450.93   267.7 2451.71   295.7 2452.15   318.4 2456.86   334.3 2466.04
   352.4 2474.32   363.8 2480.33   389.3 2494.98   467.6 2543.93   502.6  2567.5
   528.2 2583.51   540.2 2591.87   556.5 2600.93   581.4 2616.53   593.3 2622.55
#Mann= 5 ,-1,0
       0      .1       0   139.2    .045       0   157.8      .1       0
     220     .06       0     370      .1       0
Bank Sta=139.2,157.8
XS Rating Curve= 0 ,0
Exp/Cntr=0.3,0.1

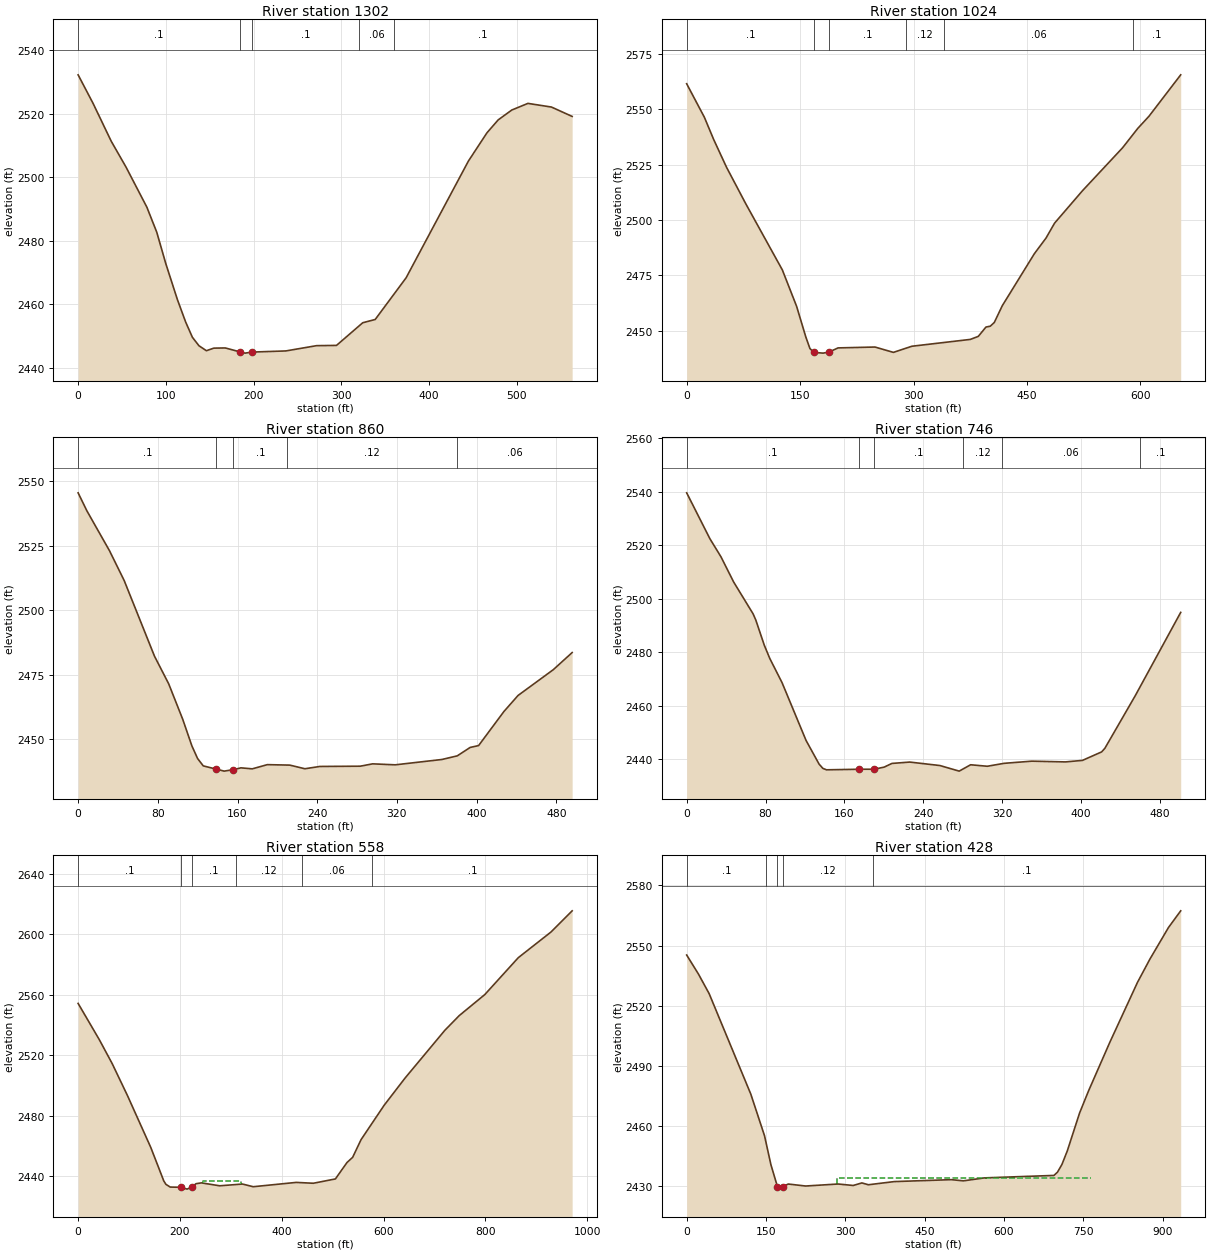
Type RM Length L Ch R = 1 ,1302    ,279.3,277.9,275.7
XS GIS Cut Line= 2
2215476.18763979391494.4685296522215873.90192149391892.856174789
#Sta/Elev= 30
       0 2532.22      17 2523.26    37.7 2511.34    54.7 2503.13    78.3 2490.59
    89.6  2482.7    99.9 2472.81   113.2 2461.43   122.5 2454.45   130.2 2449.63
   137.7 2446.96   146.2  2445.4   154.6 2446.21   167.7 2446.27   184.7 2445.01
   190.3 2444.64   198.1 2444.97   236.7 2445.33   271.7 2446.99   294.4 2447.07
   324.3  2454.2   338.5 2455.23   373.7 2468.34   444.7 2505.08   465.8 2513.96
   478.6 2518.03   494.1 2521.14   512.5 2523.23   539.3 2522.08   562.9 2519.13
#Mann= 5 ,-1,0
       0      .1       0   184.7    .045       0   198.1      .1       0
     320     .06       0     360      .1       0
Bank Sta=184.7,198.1
XS Rating Curve= 0 ,0
Exp/Cntr(USF)=0,0
Exp/Cntr=0.3,0.1

Type RM Length L Ch R = 1 ,1024    ,162,164.1,164.6
XS GIS Cut Line= 2
2215249.15330291391653.8071861362215742.19043123392082.446673422
#Sta/Elev= 30
       0 2561.51    23.4 2546.38    35.6 2536.41    52.7  2523.8    78.2 2507.28
   126.5 2477.45   145.4 2460.97   157.6 2447.11     163 2441.92   168.3 2440.18
   180.3 2439.86     188  2440.3   200.2 2442.22     249 2442.61   273.4  2440.2
   297.8 2442.97     375 2446.05   385.6 2447.42   395.8 2451.64   401.5 2452.03
   406.8 2453.71   417.4  2461.3   459.8 2484.77   475.2 2491.83   486.5 2498.56
   523.4  2513.2   576.4 2532.58   596.5 2541.34   611.3 2546.82   653.3 2565.54
#Mann= 6 ,-1,0
       0      .1       0   168.3    .045       0     188      .1       0
     290     .12       0     340     .06       0     590      .1       0
Bank Sta=168.3,188
XS Rating Curve= 0 ,0
Exp/Cntr=0.3,0.1

Type RM Length L Ch R = 1 ,860     ,112.6,113.5,113.1
XS GIS Cut Line= 2
2215160.30813481391776.5506569722215511.62742787392126.523223177
#Sta/Elev= 30
       0 2545.48     8.8 2538.51    31.5 2523.05    46.2 2511.54    76.7 2482.17
    90.9 2471.51     105 2457.76   114.2 2447.45   119.9 2442.57   125.6 2439.71
   138.9 2438.41   146.6 2437.67   155.9 2438.25   163.5 2438.94   174.8 2438.55
   189.9 2440.18   212.5    2440   227.6 2438.59   242.6 2439.48   283.2 2439.58
   295.6 2440.49   318.3 2440.11   365.2 2442.18   380.6 2443.59   393.5 2446.84
     402 2447.57   427.4 2460.76   441.6 2466.98     477 2476.98   495.9  2483.6
#Mann= 5 ,-1,0
       0      .1       0   138.9    .045       0   155.9      .1       0
     210     .12       0     380     .06       0
Bank Sta=138.9,155.9
XS Rating Curve= 0 ,0
Exp/Cntr(USF)=0,0
Exp/Cntr=0.3,0.1

Type RM Length L Ch R = 1 ,746     ,180.3,188.6,194.1
XS GIS Cut Line= 2
2215079.44745397391846.6489486992215435.43929269392199.359756646
#Sta/Elev= 30
       0 2539.66    23.5 2522.52    34.8  2515.7    47.6 2506.31    67.4 2494.34
    70.2 2491.96    78.7 2482.64    84.3 2477.66    96.7 2468.64   121.1 2446.97
   134.3 2438.12   138.1 2436.53   141.8 2435.98   174.8 2436.19   190.12436.203
   200.3 2436.99   208.2 2438.37   226.3 2438.88   256.9 2437.58   276.4 2435.49
     288 2437.87   304.9 2437.31     322 2438.41   350.1 2439.22   384.1 2438.94
   401.4  2439.5   420.9 2442.69   424.2 2444.05   454.9 2463.66   501.1 2494.91
#Mann= 6 ,-1,0
       0      .1       0   174.8    .045       0   190.1      .1       0
     280     .12       0     320     .06       0     460      .1       0
Bank Sta=174.8,190.1
XS Rating Curve= 0 ,0
Exp/Cntr(USF)=0,0
Exp/Cntr=0.3,0.1

Type RM Length L Ch R = 1 ,558     ,127.5,129.8,131.3
XS GIS Cut Line= 4
  2214984.171742391865.8410825392215060.89388579392092.321391484
2215241.85847717 392291.228618252215690.87064353392401.330213406
#Sta/Elev= 30
       0 2554.29    41.5 2530.43    66.9 2514.55    97.3 2493.16   142.9 2459.03
   168.2  2437.1   172.5 2434.79   180.9    2433202.49582432.871     214 2431.64
222.79542432.987   231.6 2435.22   242.1 2435.77   278.1 2433.84   322.7    2435
     344 2433.23   428.3 2436.08     462 2435.52   505.3 2438.37   528.1 2449.22
   539.2 2452.65   555.7 2464.31     601    2487   642.2 2505.02   720.5 2536.62
   748.6 2546.26   798.7 2560.12   864.6 2584.52   928.7 2601.44   970.3 2615.44
#Mann= 6 ,-1,0
       0      .1       0202.4958    .045       0222.7954      .1       0
  309.12     .12       0  439.12     .06       0  578.03      .1       0
#XS Ineff= 1 ,-1
  244.45  319.83 2436.72
Permanent Ineff=
       F
Bank Sta=202.4958,222.7954
XS Rating Curve= 0 ,0
Exp/Cntr(USF)=0,0
Exp/Cntr=0.3,0.1

Type RM Length L Ch R = 1 ,428     ,106.8,114.8,120.2
XS GIS Cut Line= 4
2214935.33880394 391894.893197882214918.59570391392045.581098128
2214979.58842544392326.625991448 2214678.3585498392719.402438307
#Sta/Elev= 30
       0 2545.33    22.4 2535.78    42.5 2526.07   121.3 2475.95   147.2 2455.22
   159.3 2440.77   171.7 2429.79   175.8  2428.6  181.56 2429.83   192.1 2431.14
   224.9 2430.15   286.3 2431.15   314.9 2430.42   331.3 2431.69   343.6 2430.78
   392.7 2432.36   500.5 2433.32   523.3 2432.73   563.3 2434.21   694.5 2435.43
   701.2 2437.07   709.6 2440.91   719.7 2447.63     743 2466.58     760 2477.63
   799.7 2501.54   852.3 2531.61   875.9 2543.27   911.2  2559.1   934.2 2567.37
#Mann= 5 ,-1,0
       0      .1       0     150     .12       0   171.7    .045       0
  181.56     .12       0  351.62      .1       0
#XS Ineff= 1 ,-1
  283.65   763.8 2434.12
Permanent Ineff=
       F
Bank Sta=171.7,181.56
XS Rating Curve= 0 ,0
Exp/Cntr(USF)=0,0
Exp/Cntr=0.3,0.1

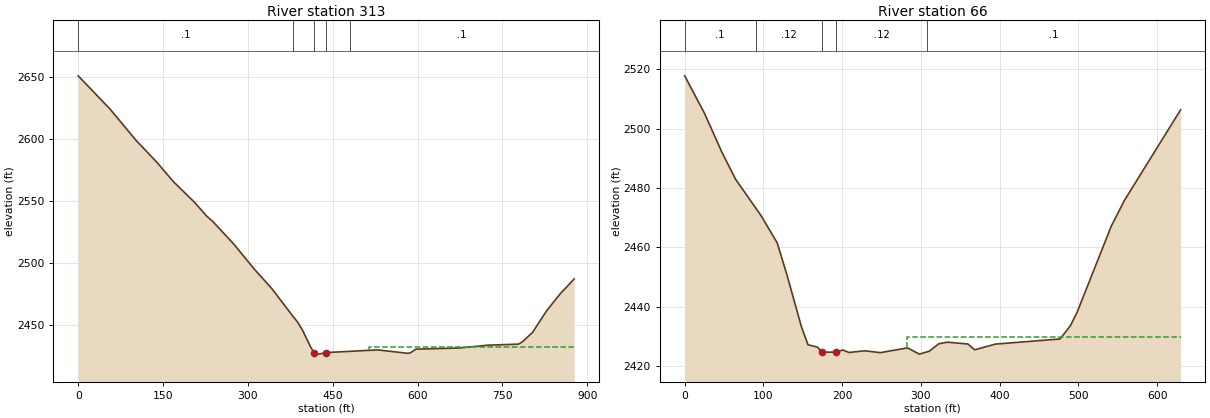
Type RM Length L Ch R = 1 ,313     ,250.5,247,243.8
XS GIS Cut Line= 2
 2214928.3989264 391682.958742282214694.58755929392528.062178406
#Sta/Elev= 30
       0 2651.27    56.3 2624.43   101.9 2599.35   139.3 2581.34   168.3 2565.84
   205.7 2549.08   226.6 2538.27   238.9  2533.2   275.1 2515.38   310.8 2495.45
   342.6 2479.31     380 2456.86   388.3 2452.12   396.6 2445.92   411.6 2431.72
   417.3 2427.75   425.6 2426.52   437.6 2427.76   529.4 2429.94   583.3 2427.16
   587.5 2427.64   596.9 2430.52   674.2 2431.49   724.4 2433.74   778.4  2434.6
   785.4 2436.43   803.3 2444.08   828.2 2461.49     852 2475.09   876.9 2487.26
#Mann= 5 ,-1,0
       0      .1       0     380     .12       0   417.3    .045       0
   437.6     .12       0     480      .1       0
#XS Ineff= 2 , 0
                          514.34         2432.24
Permanent Ineff=
       F       F
Bank Sta=417.3,437.6
XS Rating Curve= 0 ,0
Exp/Cntr=0.3,0.1

Type RM Length L Ch R = 1 ,66      ,,,
XS GIS Cut Line= 5
2214641.50362672 391862.044080312214578.81194659392001.389627326
2214572.78945936392126.1847585962214533.32391904392154.319336501
2214416.06901433 392434.40207211
#Sta/Elev= 30
       0 2517.85    25.4 2505.08    47.3 2492.05    64.8 2482.88    97.2  2470.6
   117.5 2461.48     130 2450.58   148.2 2433.22   156.6  2427.1   168.6 2426.32
  174.562424.611   191.9 2424.61   200.6 2425.34   208.7  2424.5   228.7 2425.06
   248.7 2424.44   282.9 2426.05   298.1 2423.94   310.5 2424.92   322.7 2427.43
   333.6 2427.97   359.7 2427.35   368.3 2425.39   394.4 2427.32   476.7 2429.05
   489.8 2433.53   498.4  2438.1   541.8 2467.15   558.5 2475.84   629.8 2506.38
#Mann= 5 ,-1,0
       0      .1       0      90     .12       0  174.56    .045       0
   191.9     .12       0  307.74      .1       0
#XS Ineff= 2 , 0
                           282.2         2429.62
Permanent Ineff=
       F       F
Bank Sta=174.56,191.9
XS Rating Curve= 0 ,0
Exp/Cntr(USF)=0,0
Exp/Cntr=0.3,0.1
LCMann Table=0

Chan Stop Cuts=-1
Use User Specified Reach Order=0
Composite Channel Slope=5